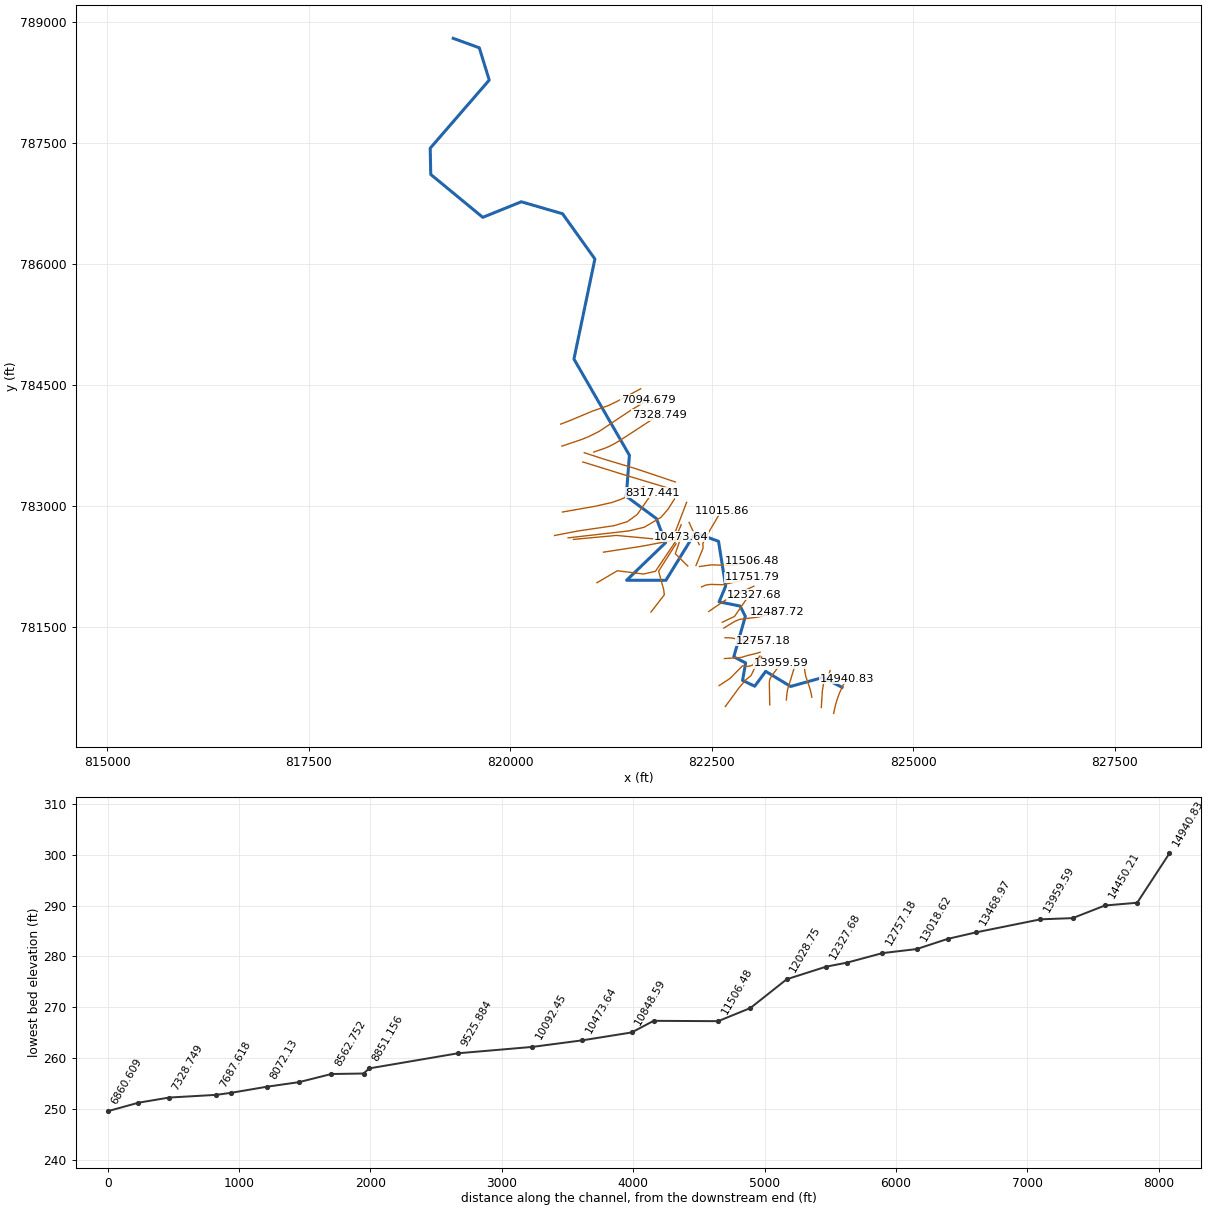
--- 17388_ras.prj (project) ---

Proj Title=17388
Current Plan=p01
Default Exp/Contr=0.3,0.1
English Units
Geom File=g01
Flow File=f01
Plan File=p01
Y Axis Title=Elevation
X Axis Title(PF)=Main Channel Distance
X Axis Title(XS)=Station
BEGIN DESCRIPTION:
RFD model 17388 exported to HEC-RAS
END DESCRIPTION:

--- 17388_ras.p01 (plan) ---

Plan Title=Plan 01
Program Version=4.10
Short Identifier=Plan 01
Geom File=g01
Flow File=f01
Subcritical Flow
Calc Critical at every XS
Secant Critical Depth

--- 17388_ras.f01 (steady flow) ---

Flow Title=Flow 01
Program Version=5.01
Number of Profiles= 6
Profile Names=10yr,25yr,50yr,100yr,100plus,500yr
River Rch & RM=17388,39,14940.83
  695.92 1077.21 1424.83 1725.74 2519.58 3452.63
River Rch & RM=17388,39,14695.52
  762.29 1182.98 1567.48 1901.29 2775.88 3764.07
River Rch & RM=17388,39,14450.21
  765.64 1188.41 1574.87 1910.46 2789.28 3780.58
River Rch & RM=17388,39, 14204.9
  772.04 1198.75 1588.96 1927.96 2814.82    3812
River Rch & RM=17388,39,13959.59
  775.36 1204.14 1596.31 1937.08 2828.14 3828.42
River Rch & RM=17388,39,13468.97
  794.37 1234.95 1638.29 1989.23 2904.28 3921.94
River Rch & RM=17388,39,13252.94
 1234.86 1930.46  2571.3 3131.48 4571.96 5826.67
River Rch & RM=17388,39,13018.62
 1239.38 1937.86 2581.45 3144.14 4590.44 5848.15
River Rch & RM=17388,39,12757.18
 1247.73 1951.46 2600.06 3167.32 4624.28 5887.25
River Rch & RM=17388,39,12487.72
 1250.84 1956.57  2607.1 3176.15 4637.18 5902.36
River Rch & RM=17388,39,12327.68
 1253.38 1960.79 2612.92 3183.46 4647.86 5914.94
River Rch & RM=17388,39,12028.75
 1272.52 1992.18 2656.05 3237.38 4726.57 6006.44
River Rch & RM=17388,39,11751.79
 1278.86 2002.67 2670.55 3255.58 4753.15 6037.65
River Rch & RM=17388,39,11506.48
  1281.9  2007.7  2677.5 3264.32  4765.9 6052.61
River Rch & RM=17388,39,11015.86
 2665.16 4249.32 5737.11 7065.7310315.9612006.55
River Rch & RM=17388,39,10848.59
 2667.97 4253.97 5743.54 7073.8110327.7612018.93
River Rch & RM=17388,39,10473.64
 2670.36 4257.91 5748.99 7080.6510337.7412029.39
River Rch & RM=17388,39,10092.45
 2672.09 4260.78 5752.95 7085.62   10345   12037
River Rch & RM=17388,39,9525.884
 2730.74 4357.64  5886.8 7253.6910590.3912293.68
River Rch & RM=17388,39,8851.156
 2735.88 4366.14 5898.57 7268.49   1061212316.31
River Rch & RM=17388,39,8562.752
 2741.63 4375.68 5911.78 7285.1110636.2612341.75
River Rch & RM=17388,39,8317.441
 2752.19 4393.22 5936.11 7315.76   10681 12388.8
River Rch & RM=17388,39, 8072.13
  2759.3 4405.07 5952.57 7336.5210711.3212420.76
River Rch & RM=17388,39,7802.798
  2764.3  4413.4 5964.15 7351.1410732.66 12443.3
River Rch & RM=17388,39,7687.618
 2767.41  4418.6 5971.37 7360.2610745.9812457.38
River Rch & RM=17388,39,7328.749
  2782.7 4444.15 6006.93 7405.1910811.5812526.74
River Rch & RM=17388,39,7094.679
 2787.66 4452.43 6018.46 7419.7510832.84 12549.2
River Rch & RM=17388,39,6860.609
 2789.93 4456.22 6023.73 7426.4210842.5812559.49
River Rch & RM=17388,39,6626.538
 2798.95 4471.32 6044.77 7453.0310881.4212600.62
River Rch & RM=17388,39,6392.468
 2804.24  4480.2 6057.16 7468.7110904.32 12624.9
River Rch & RM=17388,39,6158.398
 2805.87 4482.93 6060.96 7473.5310911.3512632.37
River Rch & RM=17388,39,5924.328
 2807.29 4485.31 6064.29 7477.7510917.51 12638.9
River Rch & RM=17388,39,5698.909
 2810.54 4490.77  6071.9 7487.3910931.5812653.83
River Rch & RM=17388,39,5559.402
 2813.79 4496.22 6079.51 7497.0210945.6512668.74
River Rch & RM=17388,39,5089.069
 2816.44 4500.65 6085.69 7504.8510957.0812680.86
Boundary for River Rch & Prof#=17388,39,1
Up Type= 0
Dn Type= 2
Boundary for River Rch & Prof#=17388,39,2
Up Type= 0
Dn Type= 2
Boundary for River Rch & Prof#=17388,39,2
Up Type= 0
Dn Type= 2
Boundary for River Rch & Prof#=17388,39,2
Up Type= 0
Dn Type= 2
Boundary for River Rch & Prof#=17388,39,2
Up Type= 0
Dn Type= 2
Boundary for River Rch & Prof#=17388,39,2
Up Type= 0
Dn Type= 2

--- 17388_ras.g01 (geometry) ---

Geom Title=17388
Program Version=4.10

River Reach=17388,39
Reach XY= 30
824119.406085077780749.732640652823878.852166593780870.795053284
823481.218633116780760.061526836823171.523694875780947.399481453
823035.658352408780762.891641374822884.642518939780834.964238318
  822922.7133922781052.192526581822775.582650158781126.524963747
822919.171496183781629.661460841822853.820184828 781757.63090557
822593.627023459781809.778500076  822674.8726936782003.655115385
822586.283392846782560.673143827822296.375559092782666.253790319
821933.326393306782076.747280887821446.243784251782077.876409666
 821929.55856249782543.481900795821816.404947819782842.308010582
821441.849458545 783119.00547495821480.844311447783628.445154774
820792.705499562784822.152758404821052.577474178786063.884226677
820650.903786331786624.722607935820139.807243944786773.105475088
819661.684672087786579.972219451819016.336964222787112.266314219
819009.271113399787437.295451769819741.764314683788282.842266064
819618.539129018788683.493929047819295.122966769788800.776860053

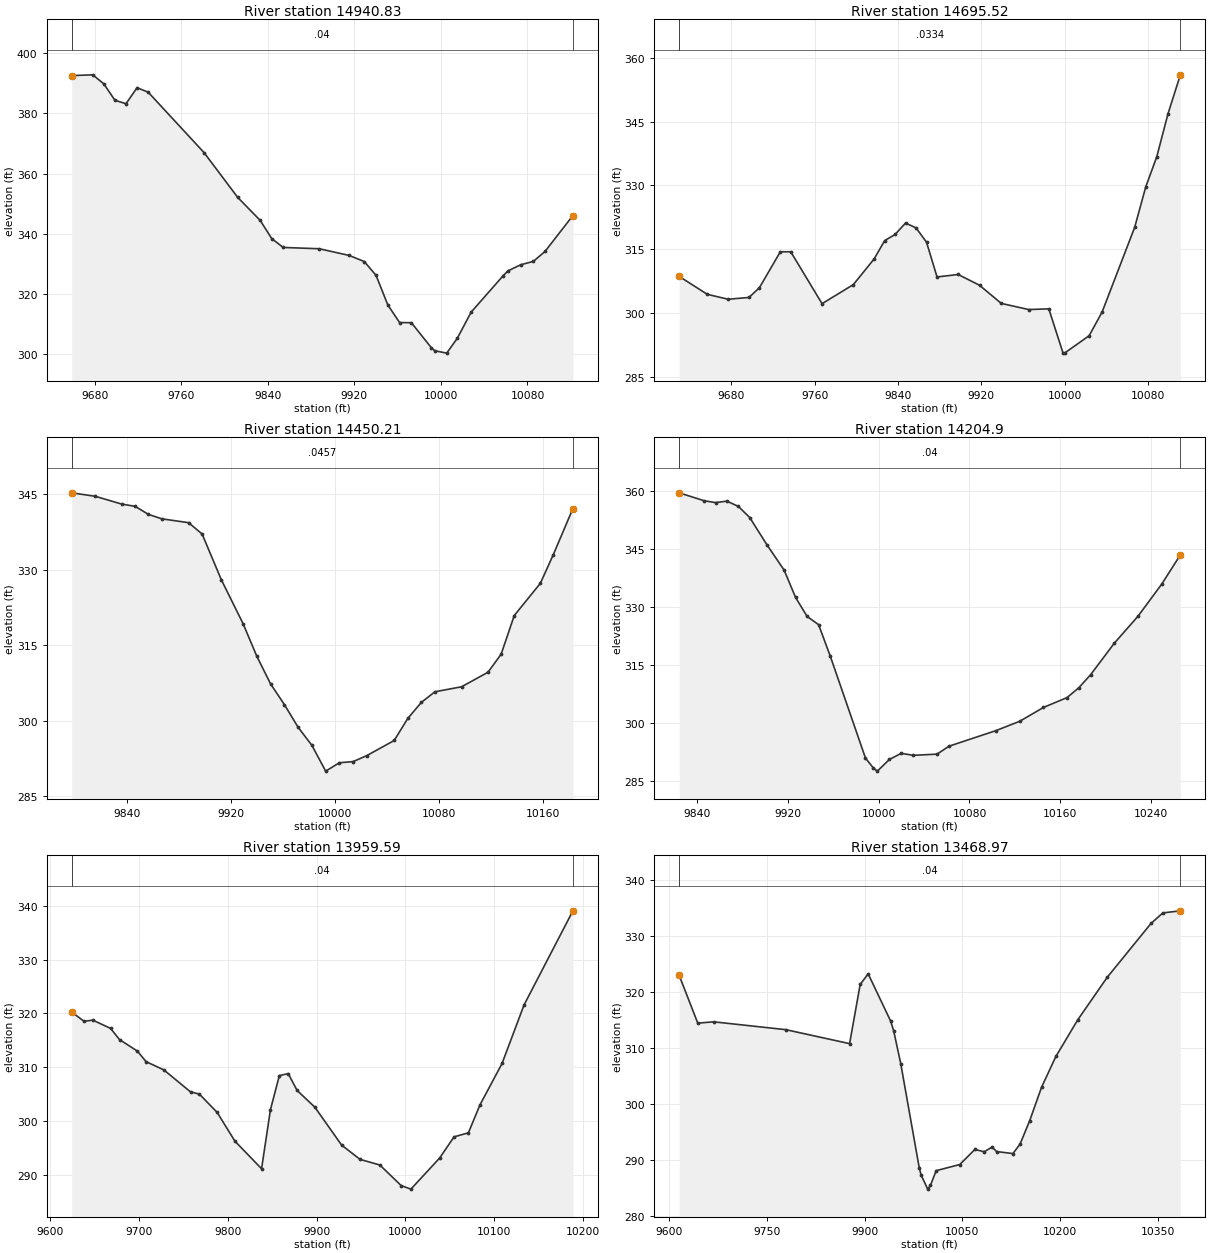
Type RM Length L Ch R = 1 ,14940.83,245.310800,245.310800,245.310800
XS GIS Cut Line= 6
824014.409355649780426.008766696824034.508734283780516.741953503
824055.589046689 780591.98943073824080.334515616780661.425063319
824121.795574272780757.721708625824178.393828648780856.259748383
#Sta/Elev= 30
9658.655392.56239678.107392.82259688.349389.80949698.592384.35979708.834383.2209
9719.077388.52969729.319387.05529780.934366.98829812.089 352.0749832.928 344.404
9843.545338.37089854.161335.42319887.555334.98849915.252332.7558 9929.11330.7325
9939.996326.15499950.882316.29659961.768310.44949972.654310.40629991.167302.0584
9994.426301.065110005.32300.284410015.08305.203610027.89313.907210057.43325.9956
10061.97327.633210073.68329.664610085.38330.780210096.19334.087910121.97 346.026
#Mann= 3 , 0 , 0
9658.655    0.04       09658.655    0.04       010121.97    0.04       0
#XS Ineff= 2 , 0
       0                               0
Bank Sta=9658.655,10121.97
Exp/Cntr=0.3,0.1

Type RM Length L Ch R = 1 ,14695.52,245.310900,245.310900,245.310900
XS GIS Cut Line= 6
823861.420928865780498.069285804823874.543876052780707.646945346
823889.032109403780794.036323936823903.875523575780828.941006465
823947.111072422 780889.55244962823971.093799292780956.263782643
#Sta/Elev= 30
9629.845308.59919656.828304.39269676.867303.22499696.907303.65739706.926305.9564
9726.965314.38619736.985 314.3889767.044302.18689797.102306.67599817.142312.7316
9827.161317.01319837.181318.45799847.241321.14349857.316320.00419867.391316.6402
9877.466308.47189897.794309.04839918.274306.52319939.142302.25769965.526300.8057
9984.808300.9774  9998.5290.57019999.917290.566810023.53294.658510035.98300.2129
10067.31320.148610077.93329.651110088.56 336.76910099.19 346.75110111.15  355.98
#Mann= 3 , 0 , 0
9629.845  0.0334       09629.845  0.0334       010111.15  0.0334       0
#XS Ineff= 2 , 0
       0                               0
Bank Sta=9629.845,10111.15
Exp/Cntr=0.3,0.1

Type RM Length L Ch R = 1 ,14450.21,245.310800,245.310800,245.310800
XS GIS Cut Line= 6
823743.542187344780626.993006707823737.551567273780663.856655765
823718.737216661 780739.25828364823669.074596211780884.825439088
823655.405782217780958.102475327823654.039101485781000.045092927
#Sta/Elev= 30
9797.352345.27579815.595344.5778 9835.87343.03619846.112342.59559856.354340.9951
9866.596340.1132 9887.26339.3517 9897.64337.10119912.441328.00629929.117319.3207
9939.711312.83859950.304307.35089960.898303.24829971.492298.73369982.086  295.15
9992.679290.030610003.26291.692610013.79291.922610024.32293.111510045.38296.1119
10055.91300.515110066.25303.671410076.69305.781810097.22306.775810117.55 309.663
10127.64313.236210137.74320.922810157.78327.304810167.78333.008710182.83342.1604
#Mann= 3 , 0 , 0
9797.352  0.0457       09797.352  0.0457       010182.83  0.0457       0
#XS Ineff= 2 , 0
       0                               0
Bank Sta=9797.352,10182.83
Exp/Cntr=0.3,0.1

Type RM Length L Ch R = 1 , 14204.9,245.310800,245.310800,245.310800
XS GIS Cut Line= 6
823427.701606199780593.059721131823433.761640441780662.884162511
823442.581170404780715.587625031823451.351852805780750.376079324
823475.177640338780823.504159002823533.966273417781020.557534388
#Sta/Elev= 30
9824.001359.45729845.997357.41319856.043 356.9319866.089357.30619876.136355.9618
9886.182353.08029901.606345.93019916.526339.49449926.665332.41649936.804327.5211
9946.943325.38269957.246317.25229988.276290.92339995.279288.33489998.785287.5433
10009.32290.548910019.84292.146210030.36 291.62710051.39291.931310061.89293.9765
10103.57298.033310124.41300.437410145.25303.999410166.09306.549510176.51309.1052
10186.94312.492410207.78320.614610228.62327.565410249.48335.835410265.99343.4215
#Mann= 3 , 0 , 0
9824.001    0.04       09824.001    0.04       010265.99    0.04       0
#XS Ineff= 2 , 0
       0                               0
Bank Sta=9824.001,10265.99
Exp/Cntr=0.3,0.1

Type RM Length L Ch R = 1 ,13959.59,490.621600,490.621600,490.621600
XS GIS Cut Line= 6
823222.106474492780531.164447688823216.734703397 780801.16528858
823219.481556958780834.088701379823225.644544012780855.963389988
823249.017547351780895.981041371823365.100973769781049.405356411
#Sta/Elev= 30
9624.069320.27219637.905318.54499647.906318.75899667.908317.21989677.909315.1432
9697.911313.01789707.912311.03039727.913309.49559757.933305.40819767.943 304.991
9787.963301.58299807.982296.23169838.012291.09999848.021 302.0919858.031308.4269
9868.041 308.8159878.051305.6755 9898.08 302.5529928.217295.50359948.995292.8413
 9971.33291.79639995.264287.9739 10006.3287.302810038.71293.093110054.92297.0321
10071.13297.787410084.05302.959910109.03310.697610133.82321.590410188.86339.1114
#Mann= 3 , 0 , 0
9624.069    0.04       09624.069    0.04       010188.86    0.04       0
#XS Ineff= 2 , 0
       09893.395                       0
Bank Sta=9624.069,10188.86
Exp/Cntr=0.3,0.1

Type RM Length L Ch R = 1 ,13468.97,216.026600,216.026600,216.026600
XS GIS Cut Line= 6
822671.148808446780511.591177233822834.153364702780734.599252968
 822922.07502471780839.440306822822989.791536242780895.036485653
 823055.84666193781031.541695426823122.917101851781126.068519017
#Sta/Elev= 30
9615.505323.01349644.028314.45269668.397314.69119779.159313.28549876.916310.7842
9893.147321.3826  9905.4323.2823 9939.85314.83199944.544313.08519955.418307.1758
9983.688288.59499986.553287.28789996.736284.7357   10001285.427910009.73288.0434
10045.94289.141110069.05291.837910083.39291.428610095.62292.272710102.41291.4623
10127.46291.103710138.45292.810210153.26297.0105 10171.4302.983510193.37308.4917
10226.93315.052710272.31322.693110339.28332.302510357.45334.192610384.31334.5646
#Mann= 3 , 0 , 0
9615.505    0.04       09615.505    0.04       010384.31    0.04       0
#XS Ineff= 2 , 0
       0                               0
Bank Sta=9615.505,10384.31
Exp/Cntr=0.3,0.1

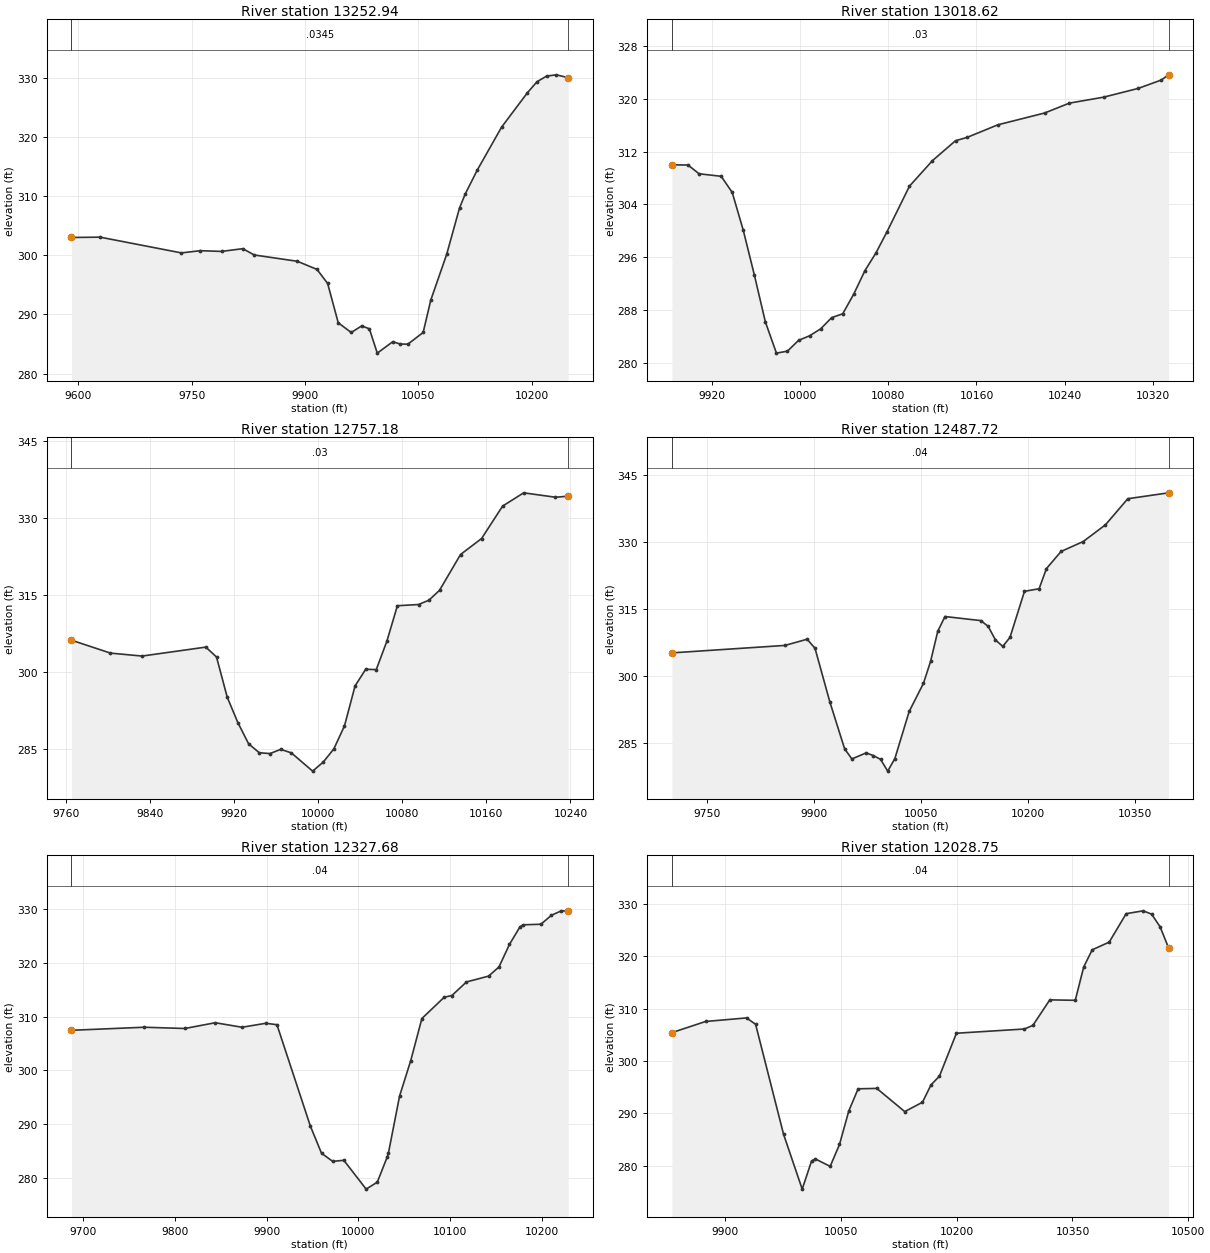
Type RM Length L Ch R = 1 ,13252.94,234.323100,234.323100,234.323100
XS GIS Cut Line= 6
822593.363660067780770.370233044822729.300594896780859.316622525
 822884.08933118781016.456710264822953.928262115781008.462430388
823008.955578744781023.472379953823099.959462374781137.196030617
#Sta/Elev= 30
9591.131303.00339628.938303.06049736.492300.3965 9761.56300.77119789.633300.6473
9817.707301.11119832.954300.04479889.953298.97969915.964297.60239930.001 295.234
9944.037288.57719961.203286.94289975.071288.05619985.213287.56149995.689283.4508
 10016.2285.3841 10026.2284.979910036.21 284.97110056.36286.941510066.49292.4258
10087.47300.140410104.49307.993810112.21310.405710128.21314.457710160.22321.6746
10194.14327.442810206.95329.335710219.76330.293810232.57330.505110248.19330.0283
#Mann= 3 , 0 , 0
9591.131  0.0345       09591.131  0.0345       010248.19  0.0345       0
#XS Ineff= 2 , 0
       0                               0
Bank Sta=9591.131,10248.19
Exp/Cntr=0.3,0.1

Type RM Length L Ch R = 1 ,13018.62,261.437400,261.437400,261.437400
XS GIS Cut Line= 5
822660.493010551781106.016985744822865.375808895 781119.55751808
822946.549318492 781143.74700366823054.144463629781169.770186588
823101.480387956781184.744305119
#Sta/Elev= 30
9883.858 309.9899898.396  309.969908.418308.63349928.462308.25139938.484305.8102
9948.506300.07149958.527293.31479968.549286.18259978.571281.45419988.593281.7528
9998.615283.385410008.64284.082410018.66285.131410028.68286.8352 10038.7287.4174
10048.72290.408210058.75293.932710068.77296.625910078.79299.825510099.23 306.758
 10120.1310.630610140.97313.6414 10151.4314.137210179.22316.045310221.76317.8418
10244.31319.342710275.18320.236910306.46321.560210327.44  322.8310334.23323.6271
#Mann= 3 , 0 , 0
9883.858    0.03       09883.858    0.03       010334.23    0.03       0
#XS Ineff= 2 , 0
       0                               0
Bank Sta=9883.858,10334.23
Exp/Cntr=0.3,0.1

Type RM Length L Ch R = 1 ,12757.18,269.456200,269.456200,269.456200
XS GIS Cut Line= 6
822667.961438415781364.477456595822739.575726805781362.513100899
822883.170388634781336.987610468822996.778794332781322.786178844
823060.462520545781321.536336026 823136.90826071781329.924878437
#Sta/Elev= 30
9765.089306.20229802.179303.68369832.232303.10749892.965304.8539 9903.14  302.92
9913.316295.08859923.491290.10179933.667285.99379943.842284.24169954.018284.0789
9964.194284.89989974.369284.21789994.643280.653310004.74282.420310014.83284.9982
10024.93289.471110035.03297.282110045.12300.5236 10055.2300.467810065.25305.9697
10075.31312.928910095.41313.163110105.42314.017710115.42315.939110135.42322.9228
10155.43326.036510175.47332.370610195.52334.959110225.82334.099610237.85334.2995
#Mann= 3 , 0 , 0
9765.089    0.03       09765.089    0.03       010237.85    0.03       0
#XS Ineff= 2 , 0
       0                               0
Bank Sta=9765.089,10237.85
Exp/Cntr=0.3,0.1

Type RM Length L Ch R = 1 ,12487.72,160.042300,160.042300,160.042300
XS GIS Cut Line= 6
822651.709244948 781483.97685467 822786.74811144781566.713520199
822849.463446267781592.761381557823052.662961209781617.156528495
823120.717681074781630.190040265823309.278227064 781684.89362763
#Sta/Elev= 30
9700.778305.23099859.169306.89579890.426308.2835 9901.49306.27039922.551294.1404
9943.057283.77619953.246281.50329973.412282.86799983.459 282.2489993.506281.4116
10003.55278.779410013.58281.586810033.65292.122610053.72298.418310063.76303.3536
10073.83310.087910083.93313.361910134.41312.443710144.59311.143210154.78308.1297
10164.96306.678310175.14308.6924 10195.5319.003210216.01319.5758 10226.3324.0811
10246.87  327.9210277.94330.138710309.17333.879310340.48339.713210397.79341.0322
#Mann= 3 , 0 , 0
9700.778    0.04       09700.778    0.04       010397.79    0.04       0
#XS Ineff= 2 , 0
       0                               0
Bank Sta=9700.778,10397.79
Exp/Cntr=0.3,0.1

Type RM Length L Ch R = 1 ,12327.68,298.935000,298.935000,298.935000
XS GIS Cut Line= 4
822633.240943342781556.983045548822784.199101896 781628.03411419
822934.085931659781845.080364883823030.968216062781898.620574668
#Sta/Elev= 30
 9687.24307.4534 9766.55308.01989810.759307.78689843.916308.85749873.091308.0167
9899.007308.7541 9911.16308.49179947.618289.66319959.771284.63169971.923283.1285
9984.076283.327810008.38277.977110020.53279.268910031.47 283.98710032.69284.6843
10044.84295.256410056.99301.824510069.15309.640910093.45313.582810101.86313.9088
10117.76316.424210141.75317.503510153.17319.2027 10164.6323.392410176.03326.6501
10179.71327.029810198.88327.1339 10210.3328.790210221.06329.622610228.55329.5488
#Mann= 3 , 0 , 0
 9687.24    0.04       0 9687.24    0.04       010228.55    0.04       0
#XS Ineff= 2 , 0
       0                               0
Bank Sta=9687.24,10228.55
Exp/Cntr=0.3,0.1

Type RM Length L Ch R = 1 ,12028.75,276.955100,276.955100,276.955100
XS GIS Cut Line= 4
822465.817894042781690.042335376822516.164906919 781725.28524442
822724.265893579781866.256880552823025.018966079782003.933890745
#Sta/Elev= 30
9831.025305.43479874.546  307.569927.634308.24319939.389307.02259975.624285.9885
9999.781275.506110011.86280.862910016.78281.278810036.02279.8603 10048.1 284.045
10060.17290.464810072.25 294.68810096.41294.768110132.64290.327610155.64292.1211
10166.64295.427710177.64297.115310199.63305.316510287.62 306.12210298.62306.8014
10320.61311.693710353.61311.6107 10364.6317.9981 10375.6321.2675 10397.6322.7355
10419.59328.176210441.59  328.7210452.59328.084510463.59325.6561 10474.6321.6171
#Mann= 3 , 0 , 0
9831.025    0.04       09831.025    0.04       0 10474.6    0.04       0
#XS Ineff= 2 , 0
       0                               0
Bank Sta=9831.025,10474.6
Exp/Cntr=0.3,0.1

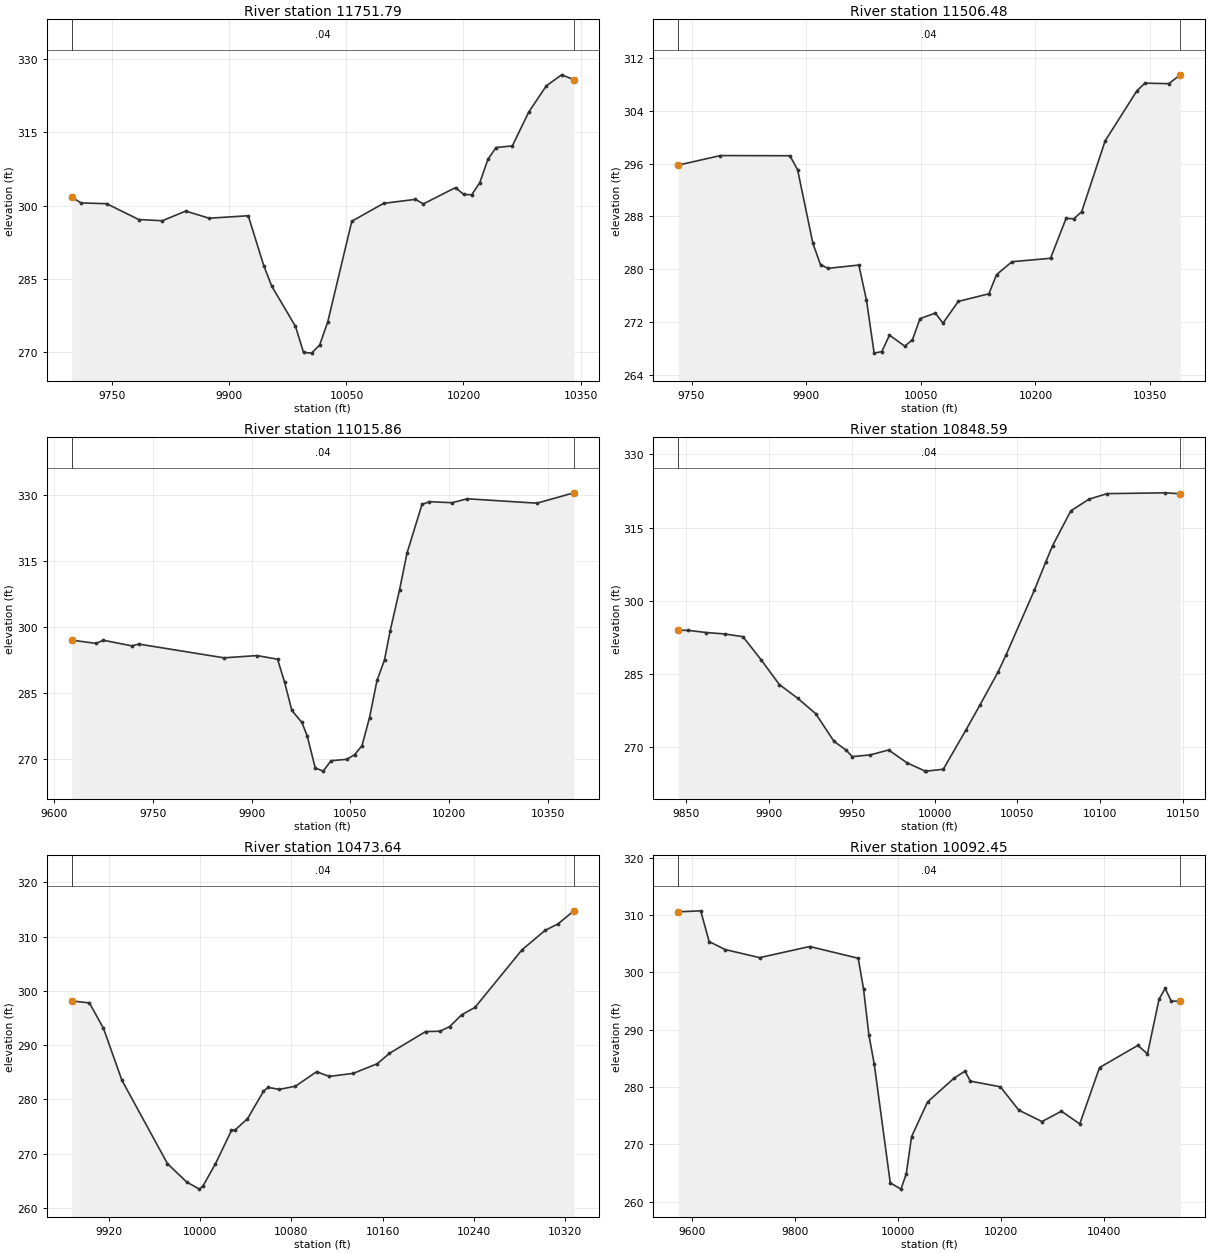
Type RM Length L Ch R = 1 ,11751.79,245.310800,245.310800,245.310800
XS GIS Cut Line= 6
822374.699994917781994.363818815822424.694194909782016.747055788
822485.114952498782025.964641518822639.418773199782022.251103807
822832.597944678782065.016801761822999.799992239782116.235846113
#Sta/Elev= 30
9697.915301.72379709.801300.53699742.633300.37669783.811297.14089813.992296.8987
9843.993298.87029874.021297.40859924.118297.91549944.153287.64679954.164283.5406
9984.662 275.3059994.972269.995110005.32269.836110015.69271.511910026.07276.2451
10056.84296.794110097.62300.448510138.41301.2648 10148.6300.3384 10189.8303.6702
10200.18302.276110210.55302.194910220.93304.683110231.31309.437110241.69311.8553
10262.63312.1921 10283.7319.123410306.17324.461910325.83326.716410341.47325.7369
#Mann= 3 , 0 , 0
9697.915    0.04       09697.915    0.04       010341.47    0.04       0
#XS Ineff= 2 , 0
       0                               0
Bank Sta=9697.915,10341.47
Exp/Cntr=0.3,0.1

Type RM Length L Ch R = 1 ,11506.48,490.621600,490.621600,490.621600
XS GIS Cut Line= 6
822350.242691547782247.906705216822502.032798946782268.675491676
822713.740575731782261.734458342822776.843878478782265.350985214
822909.369264632782289.050963849822999.407715708 782315.43864733
#Sta/Elev= 30
9732.611295.77129787.839297.21719878.707297.19229888.789295.0666 9908.79283.8997
9918.791280.65539928.792280.11429968.879280.61159978.901275.29479988.923267.2517
9998.944267.477210008.97  269.98   10029268.3131   10039269.2799   10049272.4878
   10069273.3221   10079 271.79810099.01275.095610139.07276.252910149.09279.1546
10169.19281.116210219.68281.636610240.05287.685110250.28287.630910260.51288.7201
 10291.2299.455610332.77307.051210343.18308.200310374.41308.123410389.51309.4634
#Mann= 3 , 0 , 0
9732.611    0.04       09732.611    0.04       010389.51    0.04       0
#XS Ineff= 2 , 0
       0                 10037.2       0
Bank Sta=9732.611,10389.51
Exp/Cntr=0.3,0.1

Type RM Length L Ch R = 1 ,11015.86,167.265000,167.265000,167.265000
XS GIS Cut Line= 6
822306.900617003782260.654374212  822394.6193977782476.430127442
822391.492751628782529.088817209822405.980242461782572.882009745
822580.999175608782870.144447595822628.902383149782941.668683231
#Sta/Elev= 30
9626.314297.02849663.389296.29719674.184297.01829717.363295.73779728.158296.1408
9857.695293.02219908.106  293.539939.259 292.706 9950.01287.44469960.941281.0904
9976.298278.35099984.337275.28939996.517268.043510008.57267.318710020.56269.6791
10044.55270.004910056.29 271.04110067.69273.101410079.08  279.4810090.47 287.902
10101.87292.569310110.49299.180110124.65308.388410136.05316.771910158.84327.8203
10170.23328.451410204.45328.204910227.75329.102210333.57328.102310389.74330.4518
#Mann= 3 , 0 , 0
9626.314    0.04       09626.314    0.04       010389.74    0.04       0
#XS Ineff= 2 , 0
       0                               0
Bank Sta=9626.314,10389.74
Exp/Cntr=0.3,0.1

Type RM Length L Ch R = 1 ,10848.59,374.952100,374.952100,374.952100
XS GIS Cut Line= 2
822347.151538819782519.497467786822221.283483297782795.105106667
#Sta/Elev= 30
9845.302293.94469851.351293.91269862.345293.46729873.338293.17599884.332292.6199
9895.325287.87219906.319   282.89917.312280.00859928.306276.80869939.299271.1429
9946.769269.30159950.293268.00819961.286268.3694 9972.28269.37329983.273266.7523
9994.267265.04479994.913265.032110005.26265.417710018.98273.509610027.25278.5211
10038.24285.330810043.06288.821710060.23302.162510067.13307.979210071.22311.2951
10082.21318.430210093.21320.8367 10104.2321.966210139.34322.132110148.29 321.938
#Mann= 3 , 0 , 0
9845.302    0.04       09845.302    0.04       010148.29    0.04       0
#XS Ineff= 2 , 0
       0                               0
Bank Sta=9845.302,10148.29
Exp/Cntr=0.3,0.1

Type RM Length L Ch R = 1 ,10473.64,381.188300,381.188300,381.188300
XS GIS Cut Line= 3
822204.832919955782254.138550073822050.444484323782406.321436629
822123.227603972782618.054148361
#Sta/Elev= 30
9887.242298.14029902.714297.7831 9915.09293.09459931.204283.55059971.256268.1634
9988.184 264.7769999.339263.481110002.43264.072610013.38268.163910027.42274.2907
10030.92274.439710041.46 276.441 10055.5281.488510059.41 282.22410069.55 281.854
10083.59282.440410102.14285.1061 10113.2 284.24410134.35284.8014 10155.5286.5911
10166.07288.4905 10197.8292.503110210.32292.561810218.95293.423510229.52295.6021
10241.09296.935710282.39307.550910302.61311.127110314.12312.345510327.92314.7405
#Mann= 3 , 0 , 0
9887.242    0.04       09887.242    0.04       010327.92    0.04       0
#XS Ineff= 2 , 0
       0                               0
Bank Sta=9887.242,10327.92
Exp/Cntr=0.3,0.1

Type RM Length L Ch R = 1 ,10092.45,566.570300,566.570300,566.570300
XS GIS Cut Line= 5
821748.284260273781682.901338205821913.946037531781897.145395562
821905.967365414781961.099307612821843.122870713782190.177626744
822059.266680628782529.832185149
#Sta/Elev= 30
9573.724310.57679617.398310.74889633.746305.38969664.862 303.9939731.834302.5798
9829.193304.5235 9923.41302.47129933.779297.07799944.148289.08229954.518 284.008
9985.626263.285110006.37262.183510016.73264.8577 10027.1271.354910058.21277.4179
10110.06281.5809 10130.8282.776410141.17281.039110199.67280.032110235.23275.9702
10280.42273.9791 10318.2275.778810353.76273.564510392.18283.395310466.68287.2708
10485.31285.787310507.85295.3347 10519.7297.223410531.55294.979210549.13294.9969
#Mann= 3 , 0 , 0
9573.724    0.04       09573.724    0.04       010549.13    0.04       0
#XS Ineff= 2 , 0
       0                10071.55       0
Bank Sta=9573.724,10549.13
Exp/Cntr=0.3,0.1

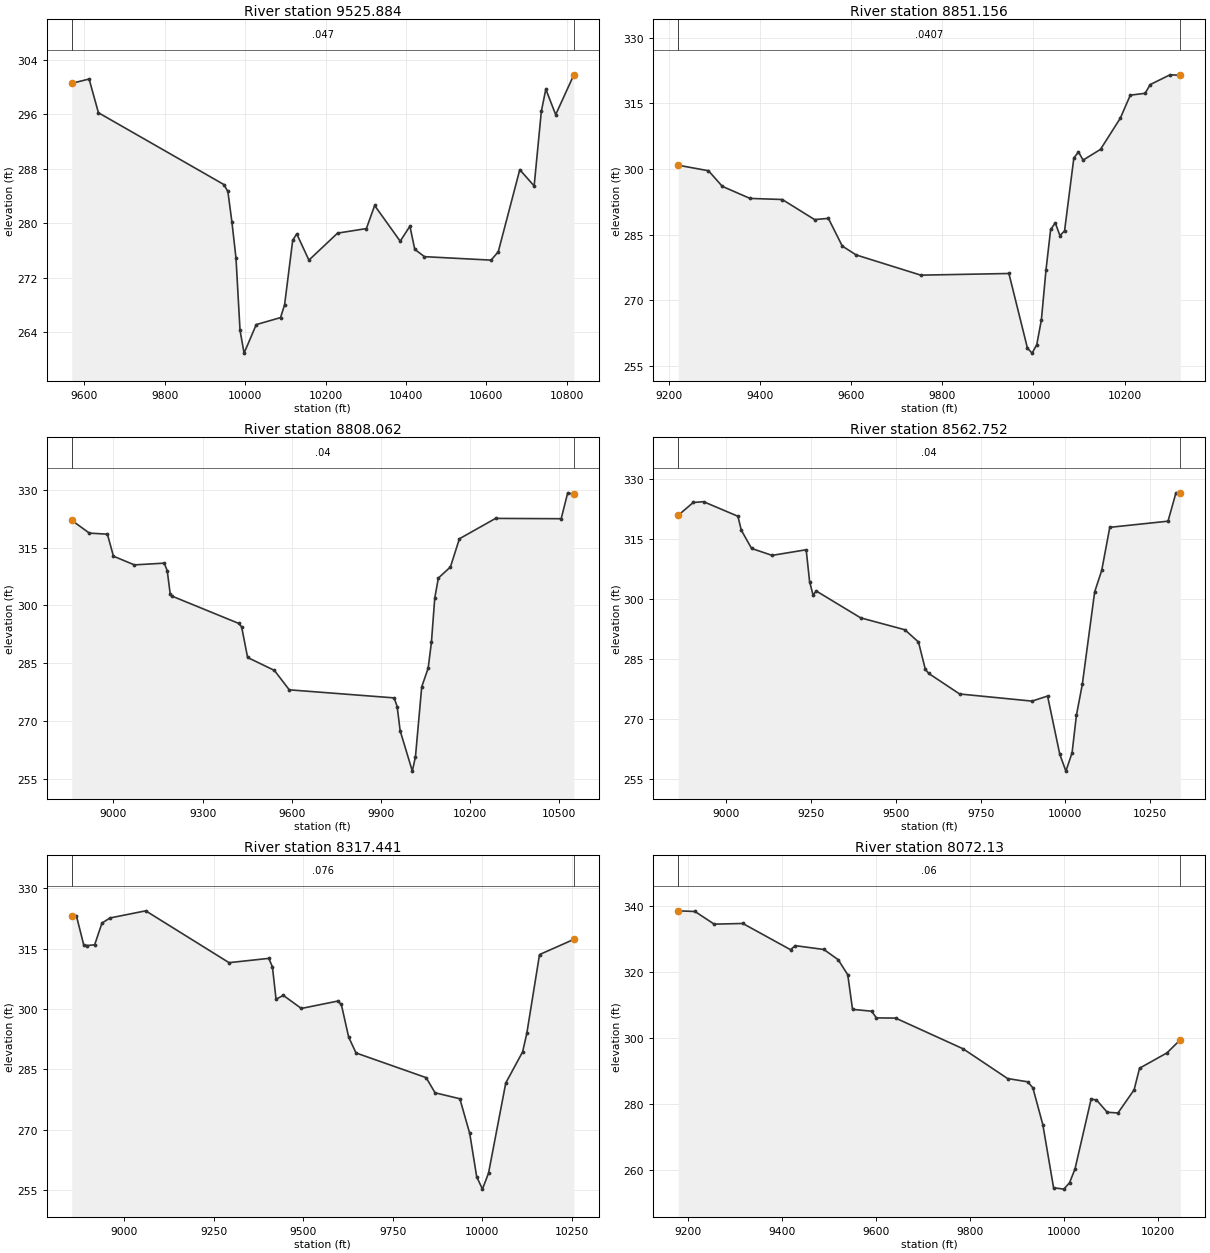
Type RM Length L Ch R = 1 ,9525.884,674.727700,674.727700,674.727700
XS GIS Cut Line= 5
821077.797339797782046.816936508821331.537278593782195.403081492
821655.651198894782154.888841435821803.422987282782187.972077668
822070.294426024782582.765363067
#Sta/Elev= 30
9568.777300.52499611.889301.15549635.065296.20819946.933285.67549957.011284.6559
9967.089280.15459977.166274.90419987.244 264.2749997.322260.926710027.56265.1153
10088.02266.1406 10098.1268.040410118.26277.504210128.33278.419810158.57274.5771
10229.78 278.53610301.51279.207910322.01282.594110385.58 277.35210409.72279.5561
10421.79 276.16110445.93275.085810611.55274.5754 10629.4275.794410682.97287.8531
10718.68285.461510736.54296.390910747.69299.663810772.25295.929410817.42301.7717
#Mann= 3 , 0 , 0
9568.777   0.047       09568.777   0.047       010817.42   0.047       0
#XS Ineff= 2 , 0
       0                10095.31       0
Bank Sta=9568.777,10817.42
Exp/Cntr=0.3,0.1

Type RM Length L Ch R = 1 ,8851.156,43.094000,43.094000,43.094000
XS GIS Cut Line= 4
 821159.40265578782426.171378344821630.053875536782498.743647426
822041.622287989782576.148715839822123.227603972 782765.82593675
#Sta/Elev= 30
9220.683300.87979287.056299.6173 9317.41296.04869378.119293.29739448.947293.0485
9519.774288.46449550.128288.73589580.483282.42499610.837280.38819752.806275.7661
9946.137276.14479986.838259.07259997.014257.951110007.19259.865310017.36265.5236
10027.54277.009110037.71286.202710047.89287.718510058.07 284.78310068.24285.9034
10088.59302.534510098.77303.912310108.94302.050110147.09304.505310190.63311.6422
10212.41316.884110245.06317.310910255.95319.2972 10299.5321.531610322.17321.4445
#Mann= 3 , 0 , 0
9220.683  0.0407       09220.683  0.0407       010322.17  0.0407       0
#XS Ineff= 2 , 0
       09921.855                       0
Bank Sta=9220.683,10322.17
Exp/Cntr=0.3,0.1

Type RM Length L Ch R = 1 ,8808.062,245.310800,245.310800,245.310800
XS GIS Cut Line= 6
820786.517811619782584.272313342821319.149946581782633.731500038
821824.257893902782586.913732823 821963.04967073782611.075216673
 822054.92354939782690.501428456822190.198705634783043.813487565
#Sta/Elev= 30
 8860.12322.1243 8919.29318.80078979.995318.5274 9000.23312.80829070.687310.5456
9171.161310.99929181.187309.03759191.212302.95799197.955302.40349421.467295.3408
9431.468294.4206 9451.47286.48119541.538283.12229591.627278.07319944.436275.9762
9954.481273.71649964.526267.447810005.53256.943310016.05260.713910037.08278.8529
10058.74283.705510069.78290.486810080.91301.920310092.99307.119510133.65310.0077
 10163.8317.333910285.48322.627810506.06322.545210528.03329.273610548.69328.8624
#Mann= 3 , 0 , 0
 8860.12    0.04       0 8860.12    0.04       010548.69    0.04       0
#XS Ineff= 2 , 0
       09929.602                       0
Bank Sta=8860.12,10548.69
Exp/Cntr=0.3,0.1

Type RM Length L Ch R = 1 ,8562.752,245.310800,245.310800,245.310800
XS GIS Cut Line= 6
820721.387579799 782603.51587918821478.435291682782690.414938094
821665.573991349782735.395575292821871.538170127782857.240425834
821958.766238692782956.693382611822040.202247059783085.981166684
#Sta/Elev= 30
8857.916 320.8048902.152324.00648932.581324.20579033.902320.56449043.989317.0727
9074.251312.51169134.775310.78589235.322312.18889245.372304.23039255.421300.9235
9265.471301.85779395.951 295.1689526.373 292.1899566.573 289.1219586.696282.3213
9596.757281.26489687.874276.13449901.333274.3505 9947.36275.61099983.292261.0785
10001.37 256.84610019.61261.430510032.38 270.78710049.88278.573410086.24301.6634
10107.01307.011710130.84317.794510302.59 319.33410326.01326.420710338.87326.3055
#Mann= 3 , 0 , 0
8857.916    0.04       08857.916    0.04       010338.87    0.04       0
#XS Ineff= 2 , 0
       09950.267                       0
Bank Sta=8857.916,10338.87
Exp/Cntr=0.3,0.1

Type RM Length L Ch R = 1 ,8317.441,245.310800,245.310800,245.310800
XS GIS Cut Line= 6
820552.422472948782633.003826534820843.306143386782688.827238266
821291.845728412782755.006717606821455.729687669782805.169811545
821578.044580292782893.716053771821766.511427004783162.922361081
#Sta/Elev= 30
 8853.91323.13128866.762323.18198887.199315.95188897.417315.75718917.854315.9461
8938.291 321.3418960.862322.60759060.458324.37729293.238311.50029404.329312.5694
9414.428310.43759424.528  302.419444.726 303.3839495.222300.12779596.622301.9556
9606.812301.15129627.378 293.0049647.943289.07289843.767282.94089868.711279.1784
9937.916277.69689965.519269.07899984.933258.339310001.03255.249110018.08259.2364
10066.19 281.61410113.24289.341210125.01293.9626 10160.5313.512410256.35317.2883
#Mann= 3 , 0 , 0
 8853.91   0.076       0 8853.91   0.076       010256.35   0.076       0
#XS Ineff= 2 , 0
       0                               0
Bank Sta=8853.91,10256.35
Exp/Cntr=0.3,0.1

Type RM Length L Ch R = 1 , 8072.13,269.332400,269.332400,269.332400
XS GIS Cut Line= 6
820649.879443142 782923.86888801821059.985948386782996.263288619
821258.538101776783041.076926767821371.230329811783079.910570916
821421.701713479783102.927809004821659.185485347783238.144813748
#Sta/Elev= 30
9179.666338.46479215.402338.26159256.102334.44189317.084334.64239418.558326.7138
9428.705327.9401 9489.59326.77559520.032323.67989540.326319.12969550.474308.6831
9591.063308.1266 9601.24 306.1049642.064306.04469785.755296.75479880.247287.7809
9923.116286.77959934.107 284.9739955.339273.80519978.177254.752410000.14254.3429
10012.29256.322210023.73260.445110058.03281.552810069.46281.296710092.33277.5759
 10115.2277.3702 10149.5284.375510161.07290.891610219.51295.531410247.78299.5019
#Mann= 3 , 0 , 0
9179.666    0.06       09179.666    0.06       010247.78    0.06       0
#XS Ineff= 2 , 0
       0                               0
Bank Sta=9179.666,10247.78
Exp/Cntr=0.3,0.1

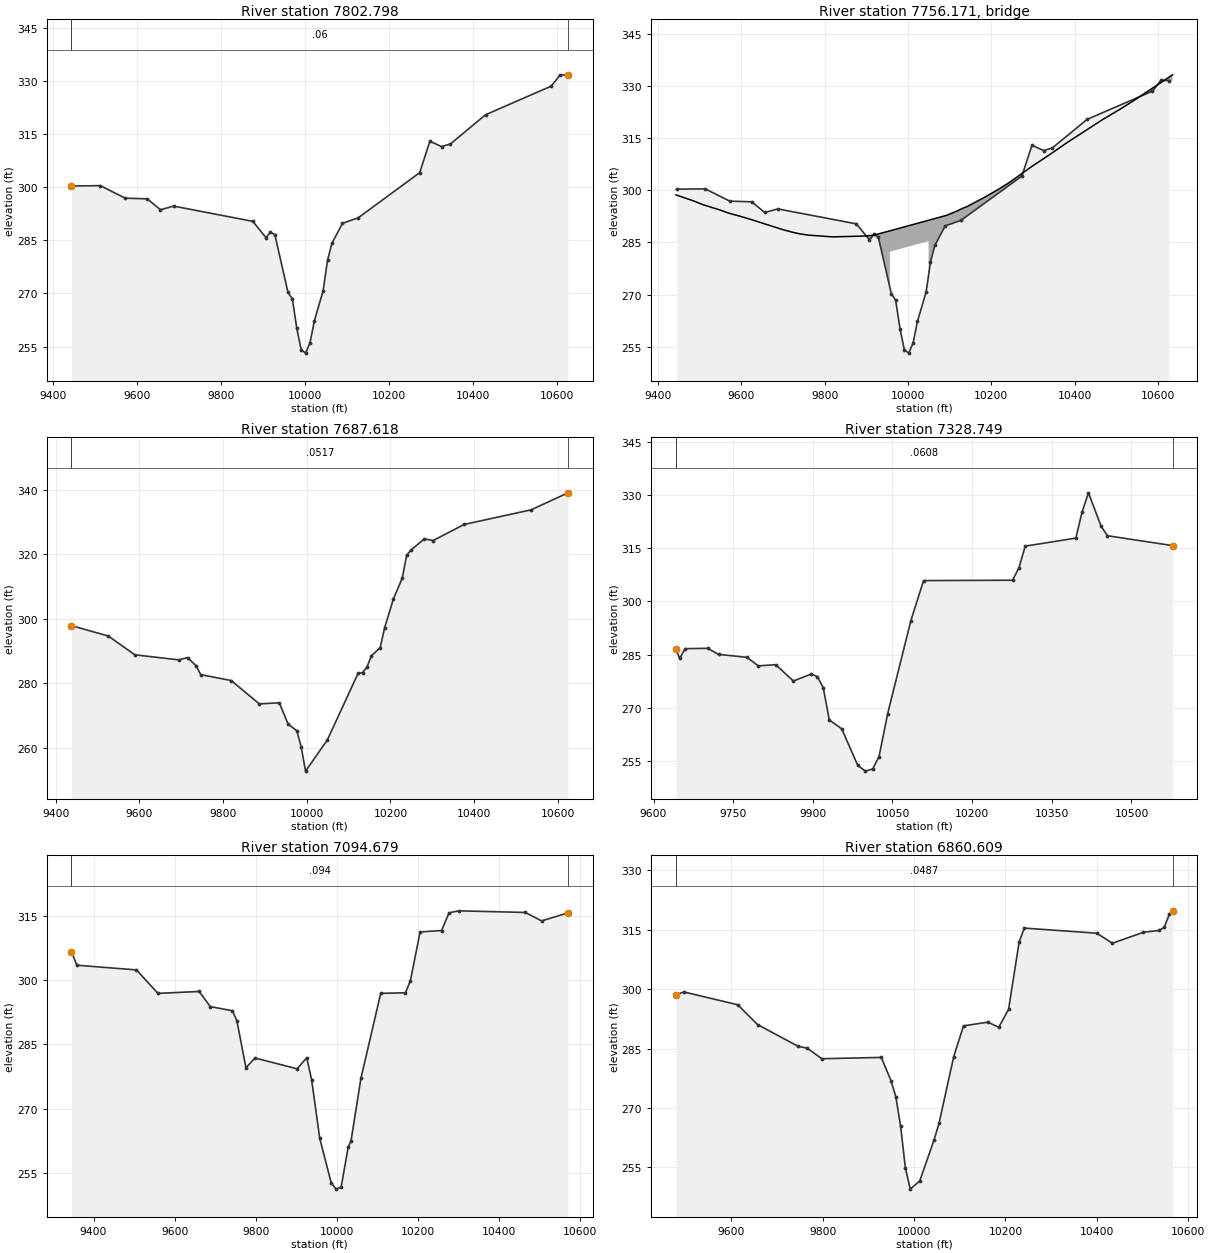
Type RM Length L Ch R = 1 ,7802.798,115.180100,115.180100,115.180100
XS GIS Cut Line= 4
820902.861279279783545.387500733821408.069057554 783388.40653494
821871.043377966783248.956438437822032.805489928783199.551261365
#Sta/Elev= 30
9444.514300.34299513.221 300.4369572.413296.89849624.771 296.7159656.186293.6414
9687.601294.6651 9876.09290.35639907.505 285.7369917.977287.30149928.449 286.638
9959.864270.27869970.335 268.3789980.787260.11629991.231254.104310001.68 253.154
10012.12256.074110022.56262.279510043.45270.787910053.89279.378310064.34284.1512
10089.38289.7835   10127291.371510273.21304.110610297.42312.966810325.43311.4691
10346.32  312.2110429.87320.445110586.68328.561310607.55331.726310626.21331.6027
#Mann= 3 , 0 , 0
9444.514    0.06       09444.514    0.06       010626.21    0.06       0
#XS Ineff= 2 , 0
       0                               0
Bank Sta=9444.514,10626.21
Exp/Cntr=0.3,0.1

Type RM Length L Ch R = 3 ,7756.171,,,
BEGIN DESCRIPTION:
END DESCRIPTION:
Bridge Culvert--1,0,-1,-1, 0
Deck Dist Width WeirC Skew NumUp NumDn MinLoCord MaxHiCord MaxSubmerge Is_Ogee
32.590050,50.000000,2.6,0, 35, 35, , , 0.95, 0, 0,0,,
 9443.21 9486.08 9507.34 9549.72 9570.84 9596.81 9627.93 9697.56 9718.68 9739.81
 9760.93 9813.73 9824.29 9887.65 9908.85 9918.56 9956.39 9956.3910049.3910049.39
10092.4310119.5510129.6810140.6310182.7810214.4010235.4810246.0110298.7110340.86
10383.5910467.1110509.1910540.7410634.82
  298.70  296.93  295.90  294.32  293.40  292.56  291.44  288.77  288.07  287.50
  287.12  286.66  286.63  286.83  286.99  287.13  288.36  288.36  291.40  291.40
  292.81  294.17  294.77  295.28  297.95  300.13  301.68  302.53  307.01  310.37
  313.90  320.39  323.39  325.77  333.26
 -701.30 -703.07 -704.10 -705.68 -706.60 -707.44 -708.56 -711.23 -711.93 -712.50
 -712.88 -713.34 -713.37 -713.17 -713.01 -712.87 -711.64  282.36  285.40 -708.60
 -707.19 -705.83 -705.23 -704.72 -702.05 -699.87 -698.32 -697.47 -692.99 -689.63
 -686.10 -679.61 -676.61 -674.23 -666.74
 9443.21 9486.08 9507.34 9549.72 9570.84 9596.81 9627.93 9697.56 9718.68 9739.81
 9760.93 9813.73 9824.29 9887.65 9908.85 9918.56 9961.64 9961.6410054.6410054.64
10092.4310119.5510129.6810140.6310182.7810214.4010235.4810246.0110298.7110340.86
10383.5910467.1110509.1910540.7410634.82
  298.70  296.93  295.90  294.32  293.40  292.56  291.44  288.77  288.07  287.50
  287.12  286.66  286.63  286.83  286.99  287.13  288.53  288.53  291.57  291.57
  292.81  294.17  294.77  295.28  297.95  300.13  301.68  302.53  307.01  310.37
  313.90  320.39  323.39  325.77  333.26
 -701.30 -703.07 -704.10 -705.68 -706.60 -707.44 -708.56 -711.23 -711.93 -712.50
 -712.88 -713.34 -713.37 -713.17 -713.01 -712.87 -711.47  282.53  285.57 -708.43
 -707.19 -705.83 -705.23 -704.72 -702.05 -699.87 -698.32 -697.47 -692.99 -689.63
 -686.10 -679.61 -676.61 -674.23 -666.74
BR Coef=-1 , 0 , 0 ,, 0 ,,,0.8,0,1,0,
WSPro=,,,, 1 ,,,, 0 ,,,, 0 ,,,,-1 ,-1 ,-1 , 0 , 0 , 0 , 0 , 0
BC Design=,, 0 ,, 0 ,,,,,,

Type RM Length L Ch R = 1 ,7687.618,358.868500,358.868500,358.868500
XS GIS Cut Line= 4
820921.213797073783659.586059268821168.731439988  783578.9748854
821549.137660275 783465.15278184822050.361150006783297.015808339
#Sta/Elev= 30
9437.973297.8375 9526.09294.61899589.192288.80469694.362287.23339715.267 287.935
9736.143285.34599746.581282.66759819.648280.82049886.578273.59649934.466273.9223
9955.342267.34049976.218265.27749986.656260.27119997.094252.744210049.28 262.434
10122.63283.085610133.18283.277610143.73284.954710154.28288.481410175.37291.0316
10185.92297.176410207.02306.140610228.11312.591510238.66319.699210249.21 321.311
10280.85324.733610301.94324.233110375.78329.203110536.04 333.75810624.03339.0171
#Mann= 3 , 0 , 0
9437.973  0.0517       09437.973  0.0517       010624.03  0.0517       0
#XS Ineff= 2 , 0
       0                               0
Bank Sta=9437.973,10624.03
Exp/Cntr=0.3,0.1

Type RM Length L Ch R = 1 ,7328.749,234.070300,234.070300,234.070300
XS GIS Cut Line= 6
821038.620648206783668.099417767 821182.02333286783717.704128694
821228.772689502783737.927586653 821301.73251259783775.532262931
821388.388064949 783828.31077468 821847.85833343784128.202677472
#Sta/Elev= 30
9642.415286.6302 9649.12283.93499659.631286.69259701.674286.77969722.696285.0836
9776.016284.23919797.436  281.849830.123282.17749863.385277.58519897.135279.5437
9908.386278.84229919.636275.70619931.018266.6203 9954.33264.14249984.569253.8462
    9999252.212510012.82252.837210024.67 256.32310040.82268.328210084.54294.5366
 10108.5305.848610276.08305.950610287.99309.390310299.91315.546610395.23317.8063
10407.14325.235710419.06330.552910442.89321.145910454.81 318.47310577.36315.6996
#Mann= 3 , 0 , 0
9642.415  0.0608       09642.415  0.0608       010577.36  0.0608       0
#XS Ineff= 2 , 0
       0                               0
Bank Sta=9642.415,10577.36
Exp/Cntr=0.3,0.1

Type RM Length L Ch R = 1 ,7094.679,234.070200,234.070200,234.070200
XS GIS Cut Line= 6
820642.245952481783741.579964379820893.380244304783825.802746863
820978.935220165783861.124433817821106.108450198783924.679799769
821484.759639992784177.809796153 821715.31328839784318.376002948
#Sta/Elev= 30
 9345.56306.62739358.901303.49069505.899302.3896 9558.93296.91149660.817297.3563
9687.995293.82779742.912292.84679753.959290.42159776.081279.5532 9798.73281.8154
9902.447279.29449926.047 281.8729938.176276.7842 9958.19 263.0579986.691252.5979
 9998.82251.194610011.04251.658410028.45260.995610035.45262.462810059.86277.0629
10108.68296.9137 10169.7 297.053 10181.9299.854710205.86311.255110258.93311.5902
10277.33315.720810301.17316.189710465.73315.810910505.83313.837510570.93315.7162
#Mann= 3 , 0 , 0
 9345.56   0.094       0 9345.56   0.094       010570.93   0.094       0
#XS Ineff= 2 , 0
       0                               0
Bank Sta=9345.56,10570.93
Exp/Cntr=0.3,0.1

Type RM Length L Ch R = 1 ,6860.609,234.070300,234.070300,234.070300
XS GIS Cut Line= 6
 820629.05649634784014.679291476820748.809455985784061.035916166
821021.732320695 784175.83557339  821213.0681626784242.176658317
821320.376332822784292.946235508821621.116934801784453.527292869
#Sta/Elev= 30
9479.015  298.599496.046 299.3089614.146296.0713 9657.54291.05869746.611285.5598
9766.027285.12479798.194282.44639928.239282.77889949.492276.92959960.096 272.838
9970.578265.3977 9981.06254.84559991.541249.517610012.49251.590910043.99262.0165
10054.59266.125810086.74282.947910108.22290.740710161.61291.6796 10185.4290.3928
10206.86294.906410230.08311.988310241.41315.430810400.12314.139710434.13311.6159
10502.15314.380510536.16314.835210547.49315.608110558.83318.958310565.76319.7925
#Mann= 3 , 0 , 0
9479.015  0.0487       09479.015  0.0487       010565.76  0.0487       0
#XS Ineff= 2 , 0
       0                               0
Bank Sta=9479.015,10565.76
Exp/Cntr=0.3,0.1