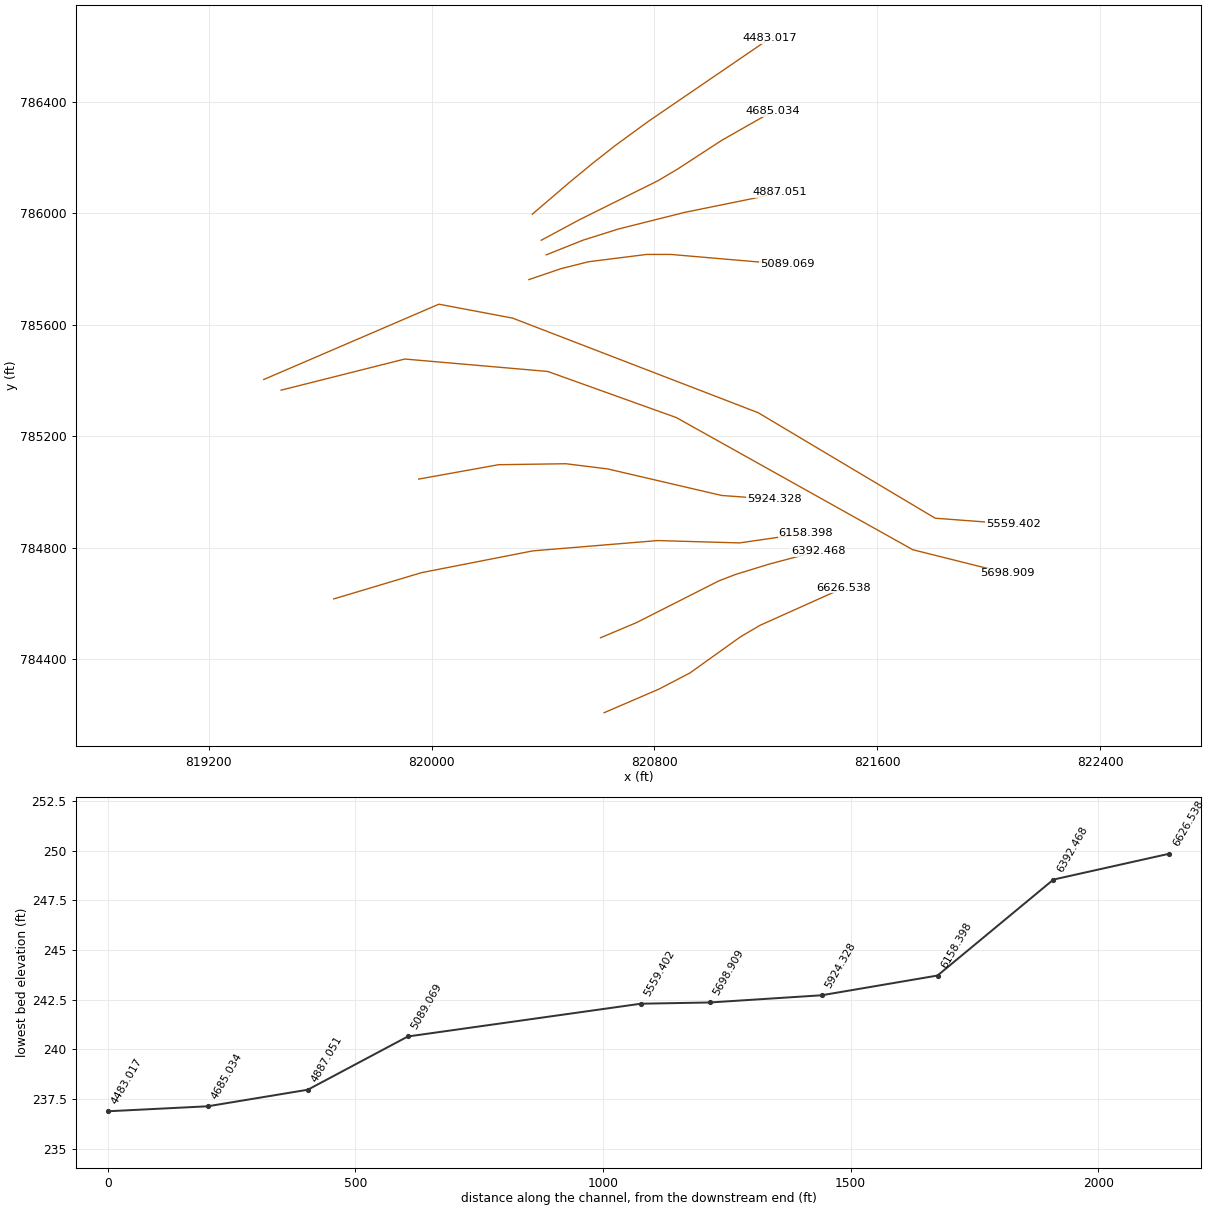
HEC-RAS study 17388_ras.prj: 17388

--- 17388_ras.g01 (geometry) --- (continued)

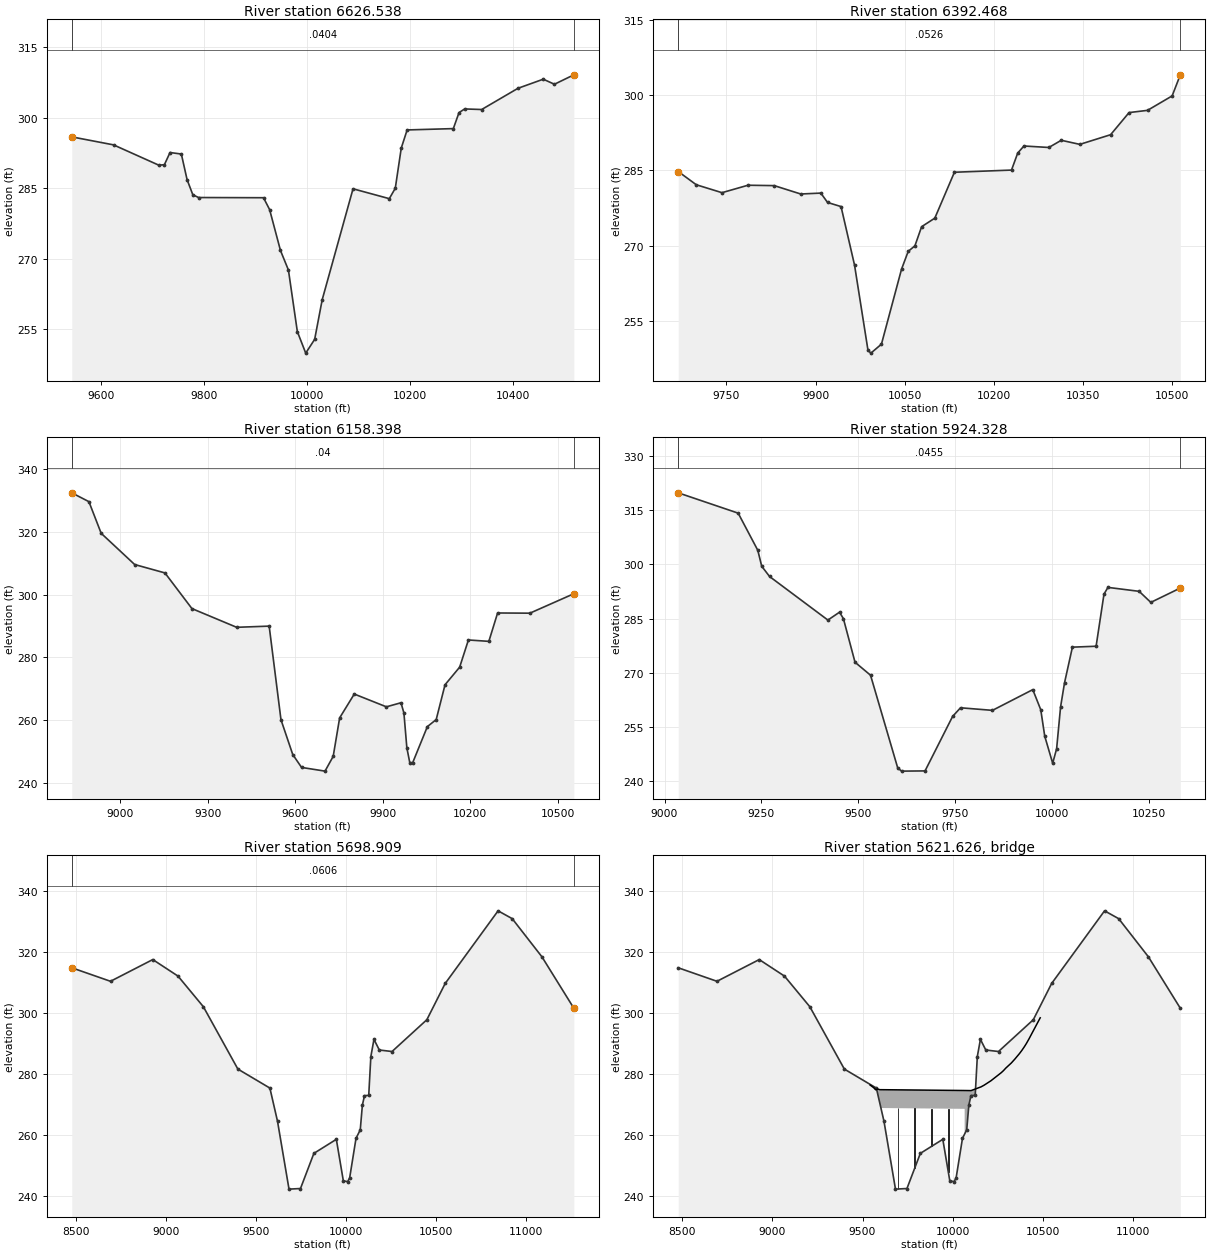
Type RM Length L Ch R = 1 ,6626.538,234.070200,234.070200,234.070200
XS GIS Cut Line= 6
820619.758998076784207.192196643 820816.63761782784291.966414064
820928.228545195784350.149579314821109.155767913784479.605467272
821179.033892763784520.742240286821480.064772815784655.906481788
#Sta/Elev= 30
9543.137295.93719624.134294.23389711.872289.9128 9722.84289.99889733.808292.6015
9755.744292.27919766.893286.82189778.077283.5908 9789.26283.0106 9915.19282.9688
 9927.06280.43069948.101271.72489963.538 267.558 9980.85254.43229997.108249.8495
10014.45252.787610029.12261.2531 10088.9284.870110159.29282.7677 10170.9284.9913
 10182.5293.553810193.88297.414710283.54297.698210294.53301.106610305.53301.8897
10338.52301.766910408.98306.290410458.05308.227210479.72307.151210517.37309.1596
#Mann= 3 , 0 , 0
9543.137  0.0404       09543.137  0.0404       010517.37  0.0404       0
#XS Ineff= 2 , 0
       0                               0
Bank Sta=9543.137,10517.37
Exp/Cntr=0.3,0.1

Type RM Length L Ch R = 1 ,6392.468,234.070300,234.070300,234.070300
XS GIS Cut Line= 6
820606.761668532784476.313373018820735.576334524784530.520612104
821031.733922424784680.599244687821092.338061532784703.878422291
821211.861034724784740.596202556821388.283084269784787.593252301
#Sta/Elev= 30
9669.021284.76749699.386282.12679742.605280.54669786.316282.03159830.449281.9538
9875.027 280.284 9908.83280.46379920.166278.5952 9942.84277.77559965.513266.1177
9988.187249.09499993.059248.547410010.79 250.33610044.57265.287210055.82 268.849
10067.08269.946310078.34273.761410100.54 275.467 10133.5284.622310229.53285.0543
10239.99288.453510250.45289.857810292.29289.561410313.22290.995910344.45290.1811
 10396.2292.109210427.24296.521610458.29296.966510499.68299.848110513.43304.0511
#Mann= 3 , 0 , 0
9669.021  0.0526       09669.021  0.0526       010513.43  0.0526       0
#XS Ineff= 2 , 0
       0                               0
Bank Sta=9669.021,10513.43
Exp/Cntr=0.3,0.1

Type RM Length L Ch R = 1 ,6158.398,234.070200,234.070200,234.070200
XS GIS Cut Line= 6
819649.010908161784615.773219813819963.919990898784710.001042488
820363.651050022784788.297445766820812.399390477784825.319554168
821106.017699086 784816.86265258821343.840692332784851.358423336
#Sta/Elev= 30
 8833.13332.50168891.944329.68238933.962  319.599048.787309.62839152.631306.9494
9245.196295.56889398.557289.60059510.078289.9768 9550.56260.11589590.929249.0132
9621.133 244.8989701.588243.71669729.667248.43389751.751260.69919801.908268.3079
9912.042264.23019962.105265.52949972.167262.26239982.229251.1563 9992.29246.4207
10002.35246.430610052.61 257.92410082.88260.159910113.15271.271110163.33276.8846
10193.33285.559710263.42285.115710293.47294.169710404.14294.106610554.91300.3118
#Mann= 3 , 0 , 0
 8833.13    0.04       0 8833.13    0.04       010554.91    0.04       0
#XS Ineff= 2 , 0
       09840.331                       0
Bank Sta=8833.13,10554.91
Exp/Cntr=0.3,0.1

Type RM Length L Ch R = 1 ,5924.328,225.418700,225.418700,225.418700
XS GIS Cut Line= 6
 819953.95911928785046.036469607820240.839854738785097.680160876
820482.124138236785101.160903821820632.121572196785082.612680297
821041.817835535784987.213840973821231.082725295784973.423391072
#Sta/Elev= 30
9035.434319.84429190.087314.21189240.708303.91799250.827299.50299271.023 296.662
9421.557284.58479451.565 286.7679461.568284.98599491.579272.89919531.609269.2985
9601.814 243.5779611.868242.72369672.226242.78449743.325257.87849763.753260.2775
9846.169259.56329950.221265.30789970.793259.73969981.079252.398910001.53244.9111
10011.72 248.927 10021.9260.493810032.09267.184710052.46277.079110113.58277.3295
10133.95291.774310144.11293.639910224.66292.546210254.76289.484910330.86293.4567
#Mann= 3 , 0 , 0
9035.434  0.0455       09035.434  0.0455       010330.86  0.0455       0
#XS Ineff= 2 , 0
       09818.276                       0
Bank Sta=9035.434,10330.86
Exp/Cntr=0.3,0.1

Type RM Length L Ch R = 1 ,5698.909,139.507000,139.507000,139.507000
XS GIS Cut Line= 6
819460.041685283785365.328657776819904.045226276785477.072276488
820417.217935681785432.491432071820878.816912949785267.012553424
821728.269874007784792.321763024822066.991386294784707.641384959
#Sta/Elev= 30
8476.537  314.768691.626310.34098926.391317.44829066.571 312.038 9207.48302.0092
9398.981281.62929576.734275.41419619.226264.52249682.965 242.3619746.704242.5581
9821.066254.05729945.798258.65039984.538245.106310008.06244.782110019.83246.0554
10055.12258.998110078.64 261.756 10090.4269.843310102.17272.934310125.69 273.025
10137.46285.7201 10154.7291.346710184.51287.864510255.08287.373310448.43297.7748
10550.17309.626810844.08333.391310922.54330.827211087.46318.352211264.75301.5332
#Mann= 3 , 0 , 0
8476.537  0.0606       08476.537  0.0606       011264.75  0.0606       0
#XS Ineff= 2 , 0
       09889.384                       0
Bank Sta=8476.537,11264.75
Exp/Cntr=0.3,0.1

Type RM Length L Ch R = 3 ,5621.626,,,
BEGIN DESCRIPTION:
END DESCRIPTION:
Bridge Culvert--1,0,-1,-1, 0
Deck Dist Width WeirC Skew NumUp NumDn MinLoCord MaxHiCord MaxSubmerge Is_Ogee
50.753500,38.000000,2.6,0, 24, 24, , , 0.95, 0, 0,0,,
 9542.30 9561.99 9572.68 9583.38 9596.38 9605.10 9605.1010067.1010067.1010102.62
10157.6710174.5710212.9110270.0910282.7810295.4810326.5710346.2510371.6310384.33
10397.0210409.7110424.0010486.71
  276.40  275.54  274.88  275.11  274.89  274.89  274.89  274.62  274.62  274.59
  275.80  276.34  277.80  280.44  281.13  281.94  283.64  284.92  286.71  287.70
  288.79  289.97  291.46  298.40
 -723.60 -724.46 -725.12 -724.89 -725.11 -725.11  268.89  268.62 -725.38 -725.41
 -724.20 -723.66 -722.20 -719.56 -718.87 -718.06 -716.36 -715.08 -713.29 -712.30
 -711.21 -710.03 -708.54 -701.60
 9542.30 9561.99 9572.68 9583.38 9596.38 9627.41 9627.4110089.4110089.4110102.62
10157.6710174.5710212.9110270.0910282.7810295.4810326.5710346.2510371.6310384.33
10397.0210409.7110424.0010486.71
  276.40  275.54  274.88  275.11  274.89  274.87  274.87  274.60  274.60  274.59
  275.80  276.34  277.80  280.44  281.13  281.94  283.64  284.92  286.71  287.70
  288.79  289.97  291.46  298.40
 -723.60 -724.46 -725.12 -724.89 -725.11 -725.13  268.87  268.60 -725.40 -725.41
 -724.20 -723.66 -722.20 -719.56 -718.87 -718.06 -716.36 -715.08 -713.29 -712.30
 -711.21 -710.03 -708.54 -701.60
Pier Skew, UpSta & Num, DnSta & Num=  ,9696.30, 2 ,9718.61, 2 , 0 , 0 , 0 ,,
    4.00    4.00
 -725.17  274.83
    4.00    4.00
 -725.18  274.82
Pier Skew, UpSta & Num, DnSta & Num=  ,9789.50, 2 ,9811.81, 2 , 0 , 0 , 0 ,,
    4.00    4.00
 -725.22  274.78
    4.00    4.00
 -725.24  274.76
Pier Skew, UpSta & Num, DnSta & Num=  ,9882.70, 2 ,9905.01, 2 , 0 , 0 , 0 ,,
    4.00    4.00
 -725.28  274.72
    4.00    4.00
 -725.29  274.71
Pier Skew, UpSta & Num, DnSta & Num=  ,9975.90, 2 ,9998.21, 2 , 0 , 0 , 0 ,,
    4.00    4.00
 -725.33  274.67
    4.00    4.00
 -725.34  274.66
BR Coef=-1 , 0 , 0 ,, 0 ,,,0.8,0,1,0,
WSPro=,,,, 1 ,,,, 0 ,,,, 0 ,,,,-1 ,-1 ,-1 , 0 , 0 , 0 , 0 , 0
BC Design=,, 0 ,, 0 ,,,,,,

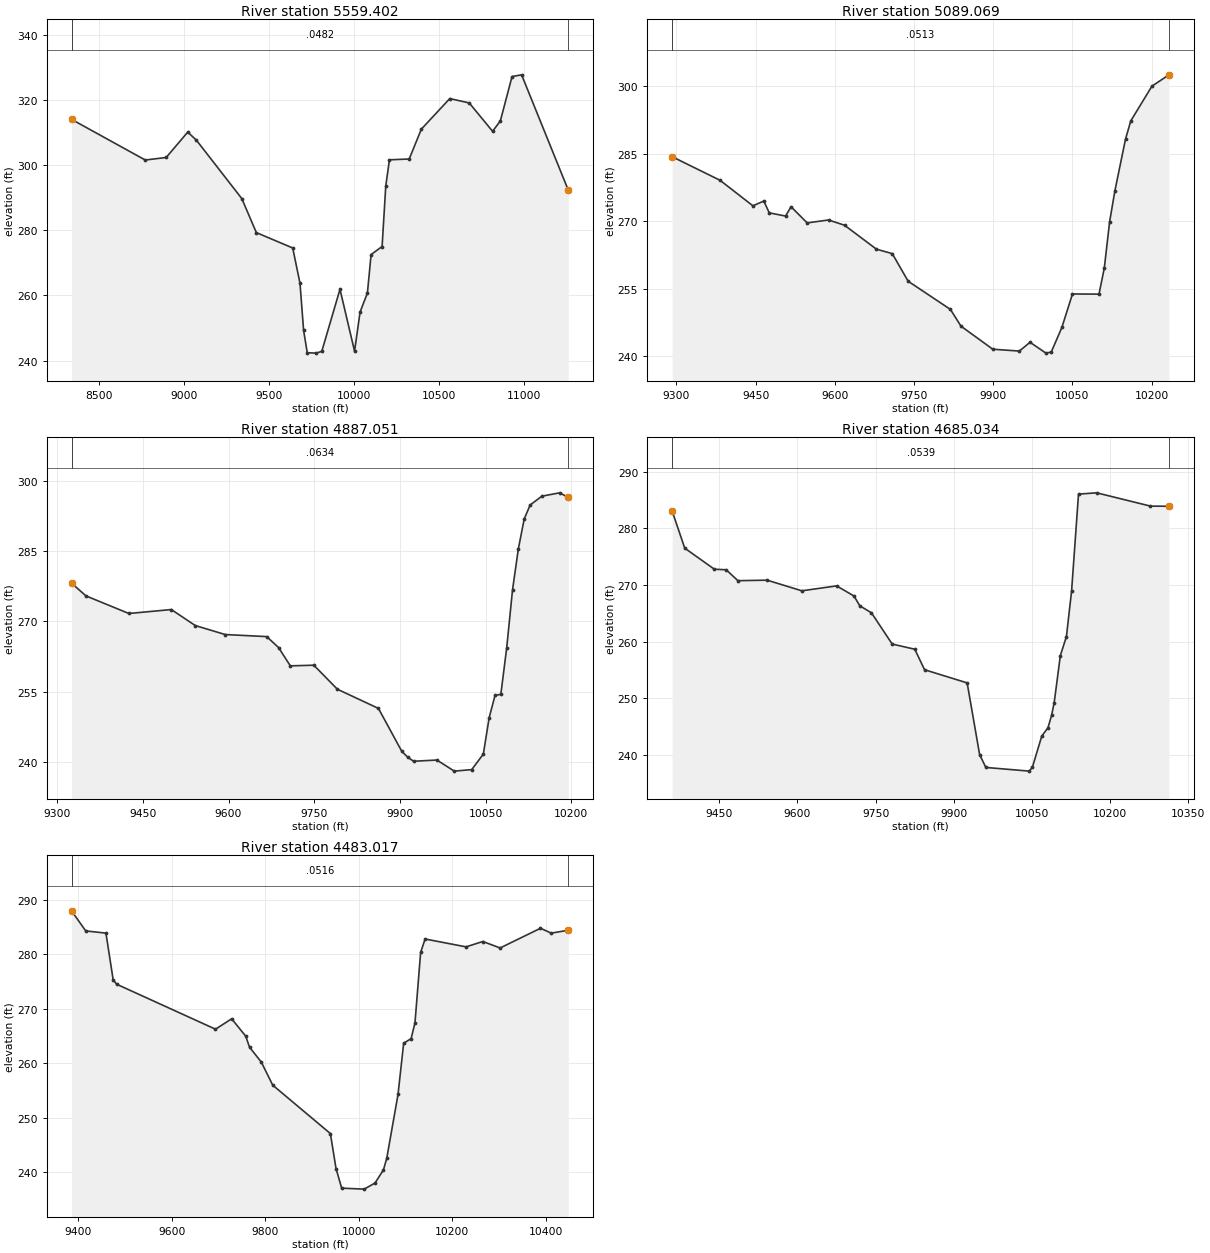
Type RM Length L Ch R = 1 ,5559.402,470.333400,470.333400,470.333400
XS GIS Cut Line= 6
819397.761146951785403.605238634820026.596292734785673.969291314
820290.931423068785624.098554716821172.759657949 785284.43138276
821808.546928495784905.571844786822088.777874909784884.501848823
#Sta/Elev= 30
8337.423314.03188771.035301.55198893.938302.32429020.846310.12399071.777307.6342
9338.623289.71629424.135279.28189637.915274.5611 9680.67263.76939702.048249.2457
9723.426242.42679776.871242.29879808.938242.86319915.828261.877410001.58242.8864
10033.95254.907510077.12260.7451 10098.7272.537710163.44 275.01210185.02293.5783
 10206.6301.614910322.75301.864410394.34311.038610561.37320.404310675.81319.0644
10813.01310.364310858.74313.566510927.34327.160110983.59327.691111258.15  292.28
#Mann= 3 , 0 , 0
8337.423  0.0482       08337.423  0.0482       011258.15  0.0482       0
#XS Ineff= 2 , 0
       0 9917.14                       0
Bank Sta=8337.423,11258.15
Exp/Cntr=0.3,0.1

Type RM Length L Ch R = 1 ,5089.069,202.017100,202.017100,202.017100
XS GIS Cut Line= 6
820349.502680027785762.232966289820465.667812007785801.748870917
820564.029638205785826.433282375820772.510025373785852.640757752
820858.912856354785852.643475256821277.232899349785816.727343545
#Sta/Elev= 30
9291.919284.32459382.495279.09129444.891273.40639465.511274.47279475.821271.8403
9506.752271.1303 9517.05273.20349547.603 269.6089588.118 270.2589618.432269.0862
9678.743263.77149708.832  262.779738.884256.6353  9818.9250.37399838.951246.6439
9899.179241.51829949.547241.10659969.694243.06359999.864240.649410009.91240.8945
   10030246.361910050.09253.804410100.32 253.76710110.37259.549710120.42269.8469
10130.46276.763410150.55288.235910160.56292.300410200.58300.017410232.84302.5366
#Mann= 3 , 0 , 0
9291.919  0.0513       09291.919  0.0513       010232.84  0.0513       0
#XS Ineff= 2 , 0
       0                               0
Bank Sta=9291.919,10232.84
Exp/Cntr=0.3,0.1

Type RM Length L Ch R = 1 ,4887.051,202.017100,202.017100,202.017100
XS GIS Cut Line= 6
820411.946405674 785851.15523531820544.298103773785903.864592496
820670.260141241785943.693450131820908.128086657786003.416617392
821165.520658377786055.815094059821249.901901224786076.426572179
#Sta/Elev= 30
9325.239278.18579350.452 275.4589425.603271.68829499.929272.53339541.881269.1098
 9594.32267.18559666.851266.74349687.553264.41039708.196260.48849749.333260.6277
 9790.47255.49499862.391251.38749903.367242.1871 9913.61240.95689923.854 240.082
 9964.71240.33979995.192237.968710025.66238.2916   10046241.620710056.22249.4189
10066.43254.147910076.65254.419710086.86264.328110097.08276.742210107.29285.5322
10117.58291.921310127.88294.894410148.46296.783510179.35297.501910194.69296.5278
#Mann= 3 , 0 , 0
9325.239  0.0634       09325.239  0.0634       010194.69  0.0634       0
#XS Ineff= 2 , 0
       0                               0
Bank Sta=9325.239,10194.69
Exp/Cntr=0.3,0.1

Type RM Length L Ch R = 1 ,4685.034,202.017200,202.017200,202.017200
XS GIS Cut Line= 6
820393.953583581785903.602397579820531.835035708 785977.57680262
820812.769177842786117.100332636820883.632546066786159.162836746
821042.730427396786262.731760001821226.202587665786367.003389739
#Sta/Elev= 30
9359.538283.0382 9383.66276.49849440.571272.7748 9463.15272.68029485.729270.7545
9541.774270.8441 9608.47268.96549675.165269.83599708.513268.04749719.629266.3195
9742.076265.07819781.805259.5693 9825.17258.65149843.947255.03379925.716252.7099
9949.619240.0611 9961.57 237.784 10045.1237.135810050.96237.839510068.93243.3264
10080.84244.792310087.75246.985310092.76249.2324 10104.6257.538510116.22260.8823
10126.11268.887210139.44286.031810174.28286.261410277.57 283.91610313.04  283.89
#Mann= 3 , 0 , 0
9359.538  0.0539       09359.538  0.0539       010313.04  0.0539       0
#XS Ineff= 2 , 0
       0                               0
Bank Sta=9359.538,10313.04
Exp/Cntr=0.3,0.1

Type RM Length L Ch R = 1 ,4483.017,0.000000,0.000000,0.000000
XS GIS Cut Line= 6
820361.883603567785997.082977622820494.215586508786110.455203652
820578.526531336786179.845978759820660.740889468786244.465778071
820778.982593821786330.681165647821215.153016664 786628.64126515
#Sta/Elev= 30
 9385.67287.9352 9416.11284.2483 9459.32 283.846 9474.69275.33219481.951274.4829
9693.643 266.2219728.231268.13039758.373264.93229766.389262.92789791.571260.1949
 9816.09255.95519939.362247.07539951.434240.66469963.505237.063310011.76 236.884
   10035238.012510052.92240.432510059.97242.549110084.07 254.25610096.12263.6503
10112.04  264.4910120.29 267.37210132.43280.310410142.01282.768110229.58281.3235
10265.38282.308310302.45281.124210388.76284.736210411.74 283.84110448.26284.3778
#Mann= 3 , 0 , 0
 9385.67  0.0516       0 9385.67  0.0516       010448.26  0.0516       0
#XS Ineff= 2 , 0
       0                               0
Bank Sta=9385.67,10448.26
Exp/Cntr=0.3,0.1